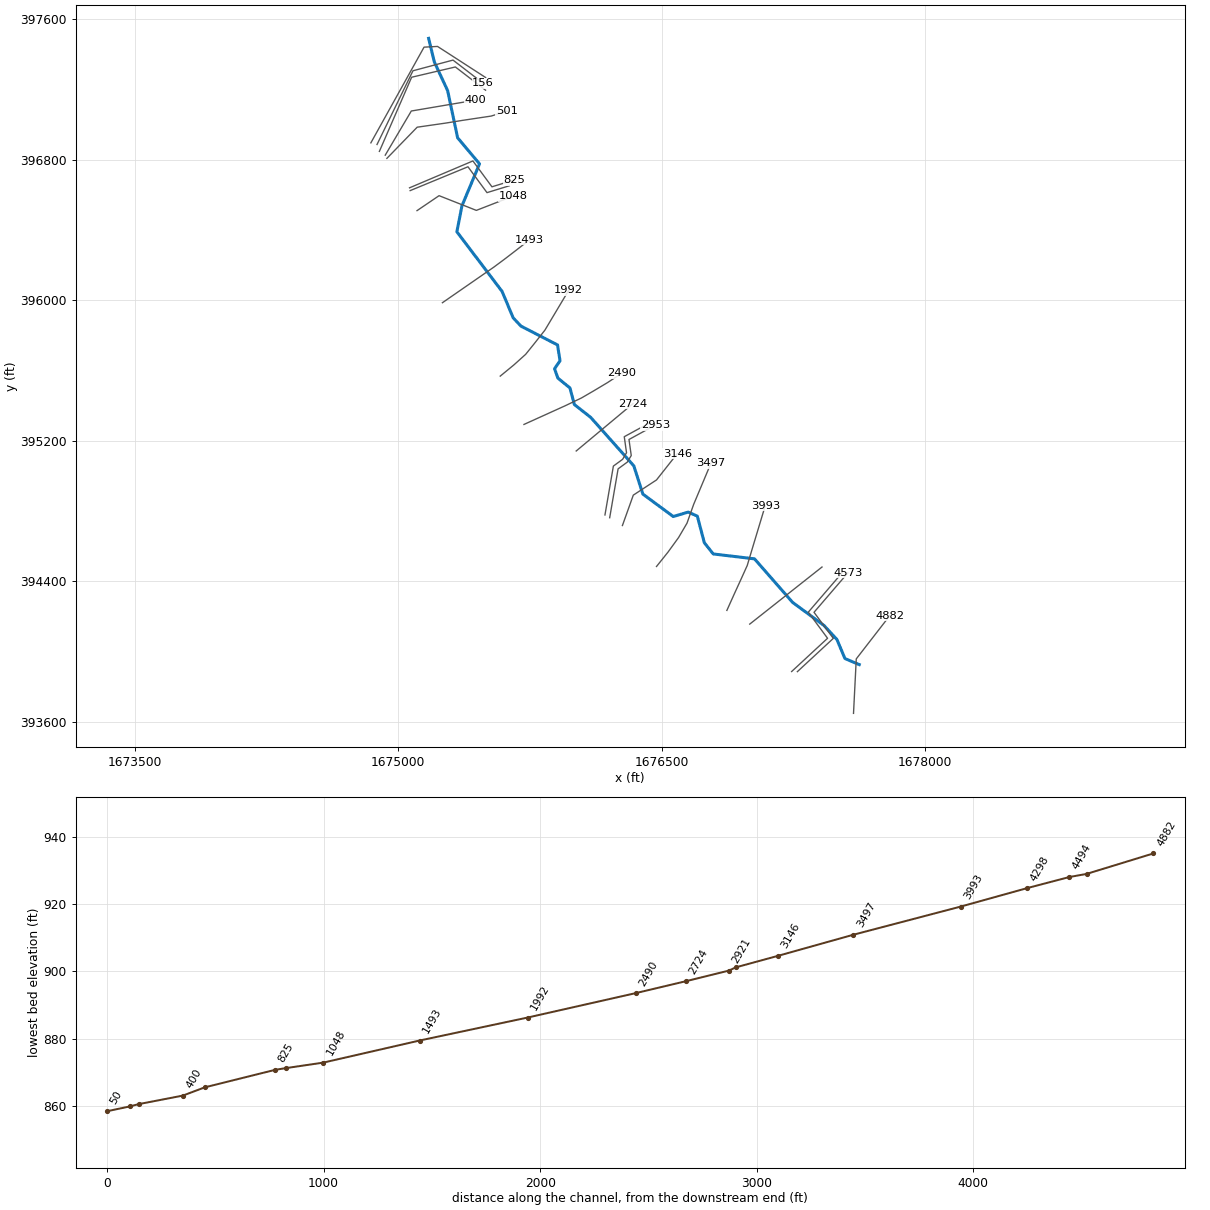
--- HYMNDRN.prj (project) ---

Proj Title=HYMNDRN
Current Plan=p01
Default Exp/Contr=0,0
English Units
Geom File=g01
Flow File=f01
Plan File=p01
BEGIN DESCRIPTION:
---------- MODELED AS PART OF WVEMD CTP PROGRAM, 2023----------
Stream Name: Haymond Run
Flood Zone:  AFH
Wetzel County, WV
HEC-RAS Version: RAS 6.3
Vertical Datum: NAVD88
Projection: NAD 1983 StatePlane West Virginia S FIPS 4702 (US Feet)
Terrain: 1-meter West Virginia FEMA R3 South Central (collected 2018-2020)
Land Use: 2019 NLCD
Hydrologic Method:
WV 2010 Regional Regression Equations
Additional Model Notes:
None
END DESCRIPTION:
DSS Export Rating Curves= 0
DSS Export Rating Curve Sorted= 0
DSS Export Volume Flow Curves= 0
DXF OffsetX= 0
DXF OffsetY= 0
DXF ScaleX= 0
DXF ScaleY= 0

--- HYMNDRN.p01 (plan) ---

Plan Title=Floodplain
Program Version=6.30
Short Identifier=Floodplain
Geom File=g01
Flow File=f01
Subcritical Flow
K Sum by GR= 0
Std Step Tol= 0.01
Critical Tol= 0.01
Num of Std Step Trials= 20
Max Error Tol= 0.3
Flow Tol Ratio= 0.001
Split Flow NTrial= 30
Split Flow Tol= 0.02
Split Flow Ratio= 0.02
Log Output Level= 0
Friction Slope Method= 1
Unsteady Friction Slope Method= 2
Unsteady Bridges Friction Slope Method= 1
Parabolic Critical Depth
Global Vel Dist= 0 , 0 , 0
Global Log Level= 0
CheckData=True
Encroach Param=-1 ,0,0, 0
Mapping Interval=1HOUR
Computation Time Step Use Courant=        0
Computation Time Step Use Time Series=    0
Computation Time Step Count To Double=0
Computation Time Step Max Doubling=0
Computation Time Step Max Halving=0
Computation Time Step Residence Courant=0
Run HTab= 0
Run UNet= 0
Run Sediment= 0
Run PostProcess= 0
Run WQNet= 0
Run RASMapper=-1
UNET Theta= 0
UNET Theta Warmup= 0
UNET ZTol= 0
UNET ZSATol= 0
UNET MxIter= 0
UNET Max Iter WO Improvement= 0
UNET MaxInSteps= 0
UNET DtIC= 0
UNET DtMin= 0
UNET MaxCRTS= 0
UNET WFStab= 0
UNET SFStab= 0
UNET WFX= 1
UNET SFX= 1
UNET Gravity=32.17405
UNET 1D Methodology=Finite Difference
UNET DSS MLevel= 1
UNET Pardiso=0
UNET DZMax Abort= 0
UNET Use Existing IB Tables= 0
UNET Froude Reduction=False
UNET Froude Limit= 0
UNET Froude Power= 0
UNET D1 Cores= 0
UNET WindReference=Eulerian
UNET WindDragFormulation=Hsu (1988)
UNET D2 Coriolis=0
UNET D2 Cores= 0
UNET D2 Theta= 1
UNET D2 Theta Warmup= 1
UNET D2 Z Tol= 0.01
UNET D2 Volume Tol= 0.01
UNET D2 Max Iterations= 20
UNET D2 Equation= 0
UNET D2 RampUpFraction=0.1
UNET D2 TimeSlices= 1
UNET D2 Turbulence Formulation=Non-Conservative (original)
UNET D2 Eddy Viscosity=0.3
UNET D2 Transverse Eddy Viscosity=0.1
UNET D2 Smagorinsky Mixing=0
UNET D2 BCVolumeCheck=0
UNET D2 Cores=0
UNET D2 SolverType=PARDISO (Direct)
UNET D2 Minimum Iterations= 3
UNET D2 Maximum Iterations= 30
UNET D2 Restart Number= 10
UNET D2 Relaxation Coeff=1.3
UNET D2 SOR Precondition Iterations= 10
UNET D2 ILUT Maximum Fill= 8
UNET D2 ILUT Tolerance=1E-08
UNET D2 Convergence Tolerance=0.00001
UNET D1D2 MaxIter= 0
UNET D1D2 ZTol=0.01
UNET D1D2 QTol=0.1
UNET D1D2 MinQTol=1
Write IC File= 0
Write IC File at Fixed DateTime=0
Write IC File at Sim End=0
Echo Input=False
Echo Parameters=False
Echo Output=False
Write Detailed= 0
HDF Write Warmup=0
HDF Write Time Slices=0
HDF Flush=0
HDF Compression= 1
HDF Chunk Size= 1
HDF Spatial Parts= 1
HDF Use Max Rows=0
HDF Fixed Rows= 1
Calibration Method= 0
Calibration Iterations= 20
Calibration Max Change=0.05
Calibration Tolerance=0.2
Calibration Maximum=1.5
Calibration Minimum=0.5
Calibration Optimization Method= 1
WQ AD Non Conservative
WQ ULTIMATE=-1
WQ Max Comp Step=1HOUR
WQ Output Interval=15MIN
WQ Output Selected Increments= 0
WQ Output face flow=0
WQ Output face velocity=0
WQ Output face area=0
WQ Output face dispersion=0
WQ Output cell volume=0
WQ Output cell surface area=0
WQ Output cell continuity=0
WQ Output cumulative cell continuity=0
WQ Output face conc=0
WQ Output face dconc_dx=0
WQ Output face courant=0
WQ Output face peclet=0
WQ Output face adv mass=0
WQ Output face disp mass=0
WQ Output cell mass=0
WQ Output cell source sink temp=0
WQ Output nsm pathways=0
WQ Output nsm derived pathways=0
WQ Create Restart=0
WQ Fixed Restart=0
WQ System Summary=0
WQ Write To DSS=0
Sorting and Armoring Iterations= 10
XS Update Threshold= 0.02
Bed Roughness Predictor= 0
Hydraulics Update Threshold= 0.02
Energy Slope Method= 1
Volume Change Method= 1
Sediment Retention Method= 0
Sediment TS Multiplier= 1
Warm Up Method= 0
XS Weighting Method= 0
Number of US Weighted Cross Sections= 1
Number of DS Weighted Cross Sections= 1
Upstream XS Weight=0
Main XS Weight=1
Downstream XS Weight=0
Number of DS XS's Weighted with US Boundary= 1
Upstream Boundary Weight= 1
Weight of XSs Associated with US Boundary= 0
Number of US XS's Weighted with DS Boundary= 1
Downstream Boundary Weight= 0.5
Weight of XSs Associated with DS Boundary= 0.5
Percentile Method= 0
Sediment Output Level= 3
Mass or Volume Output= 0
Output Increment Type= 1
Profile and TS Output Increment= 1
Transport Output Increment 1
XS Output Flag= 0
XS Output Increment= 10
Read HDF5 Sediment Hotstart= 0
Sediment Hotstart Type= 0
Write Gradation File= 0
Read Gradation Hotstart= 0
Write HDF5 File= 1
Write Binary Output= 1
Write DSS Sediment File= 0
DSS Sediment Output Type= 1
SV Curve= 0
Specific Gage Flag= 0
Subcell Erosion Methods= 0
Subcell Deposition Methods= 0
Advection Scheme= 1
Matrix Solver= 0
Implicit Weighting Factor= 1
Maximum Outer Loop Convergence Iterations= 5
Convergence Maximum Absolute= 0.001
Convergence RMSE= 0.0001
Grain Fractions Max Abs Error= 0.001
Max Subgrid Regions= 1
Max Subgrid Length Scale= 3.402823E+38
Initial Layer Thickness= 3.402823E+38
Min Layer Thickness= 3.402823E+38
Max Layer Thickness= 3.402823E+38
Number of Layers= 5

--- HYMNDRN.f01 (steady flow) ---

Flow Title=Flow
Program Version=6.31
Number of Profiles= 1
Profile Names=F01pct
River Rch & RM=HYMNDRN,Main,4882
     645
River Rch & RM=HYMNDRN,Main,2953
     772
Boundary for River Rch & Prof#=HYMNDRN,Main            , 1
Up Type= 0
Dn Type= 3
Dn Slope=0.01348
DSS Import GetInterval= 0
DSS Import GetPeak= 0
DSS Import FillOption= 0

--- HYMNDRN.g01 (geometry) ---

Geom Title=Geometry
Program Version=6.30

River Reach=HYMNDRN         ,Main
Reach XY= 30
     1677625.033      393924.209     1677543.767       393958.65
     1677497.717      394067.391     1677424.191      394147.108
     1677245.794      394278.294     1677028.699      394526.347
     1676793.802       394554.21     1676743.108      394617.674
     1676702.863      394769.757     1676651.007      394792.589
     1676565.872      394767.435     1676392.892      394895.138
     1676341.424      395055.734     1676095.693      395332.037
     1676002.818      395405.176     1675977.664      395499.599
     1675909.169      395555.324      1675889.82      395608.727
     1675921.165       395654.39     1675906.847      395744.557
     1675698.653       395851.75     1675654.537      395898.574
     1675591.073      396049.496     1675333.732      396388.876
      1675362.61      396536.484     1675462.596      396775.855
     1675337.989      396924.067     1675281.103      397192.631
     1675205.255      397356.323     1675172.822      397490.521

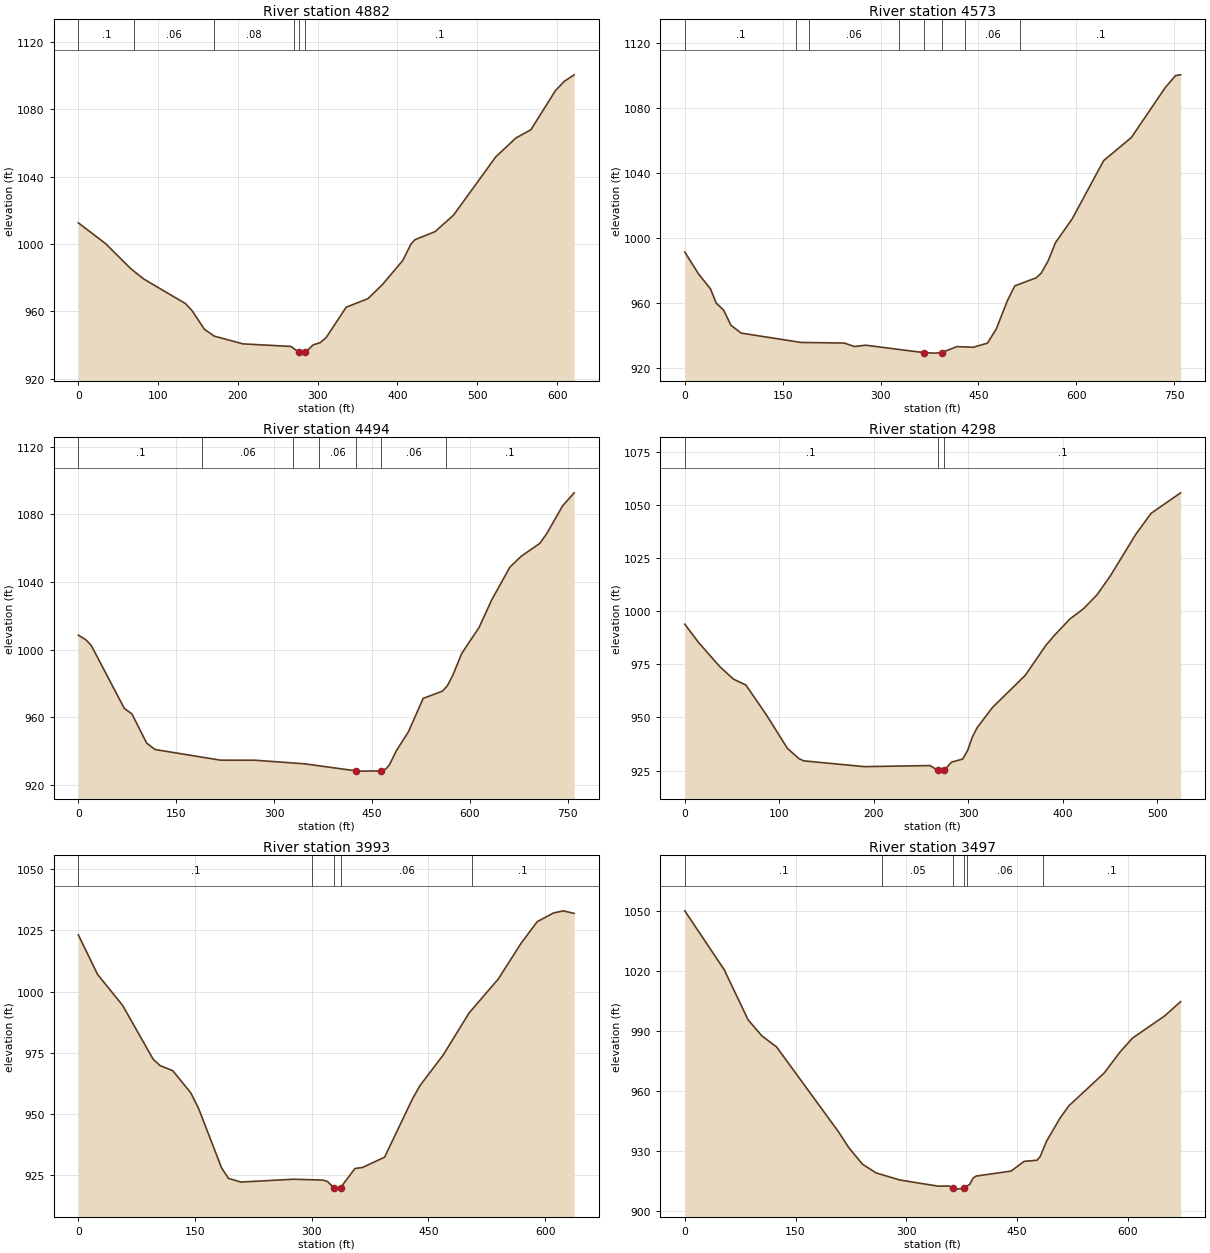
Type RM Length L Ch R = 1 ,4882    ,309.3,309.3,309.3
XS GIS Cut Line= 3
1677592.41123013393646.4305535411677608.12722776393956.768538133
1677798.40879489394202.293140878
#Sta/Elev= 30
       0 1012.54    34.2 1000.17    66.2   985.1    82.2   979.1   134.3  964.54
   142.3  960.52     158   949.3   170.3  945.23   206.4   940.6   266.4  939.09
   276.8  935.53   282.5  935.11   284.3 935.533   294.5  940.08   302.9  941.26
   310.5  944.31   335.7   962.4     363   967.5   381.3  975.94   406.6  990.18
   416.7  999.74   421.7 1002.48   447.1 1007.33   470.2 1017.09     523 1051.68
   548.3 1062.94   567.2  1067.9     598 1091.15     609 1096.62   621.4 1100.51
#Mann= 6 ,-1,0
       0      .1       0      70     .06       0     170     .08       0
     270      .1       0   276.8    .045       0   284.3      .1       0
Bank Sta=276.8,284.3
XS Rating Curve= 0 ,0
Exp/Cntr(USF)=0,0
Exp/Cntr=0.3,0.1

Type RM Length L Ch R = 1 ,4573    ,79.2,79.2,79.2
XS GIS Cut Line= 4
1677272.75749766393884.0587481191677477.40811056394073.506744064
1677367.48149563394222.024617428 1677560.4377878394446.555575585
#Sta/Elev= 30
       0  991.23    20.9  977.85    39.5  968.48      48  959.91    59.6  955.42
    70.6   946.2    86.3  941.34   178.2  935.58   244.4   935.2   259.8  933.07
   277.1  933.88   365.8929.3425   381.9     929   393.5  929.33     417  933.01
   441.9  932.61   463.7  935.13   477.2  943.86   494.2  961.21   505.6  970.42
   538.3  975.34   546.1  978.26   556.7  985.79     568  997.06   593.5 1011.64
   641.7 1047.51   684.3 1061.82   735.9 1092.39   751.8  1099.9   759.7 1100.38
#Mann= 8 ,-1,0
       0      .1       0     170     .07       0     190     .06       0
  328.88      .1       0   365.8    .045       0   393.5      .1       0
  428.88     .06       0  513.65      .1       0
Bank Sta=365.8,393.5
XS Rating Curve= 0 ,0
Exp/Cntr(USF)=0,0
Exp/Cntr=0.3,0.1

Type RM Length L Ch R = 1 ,4494    ,195.4,195.4,195.4
XS GIS Cut Line= 4
1677240.01339959393884.643464156 1677444.6640125394074.091460101
1677334.73739757394222.6093334651677527.69368973394447.140291622
#Sta/Elev= 30
       0  1008.5    11.6 1005.75    19.8 1002.39    70.5  965.14    82.1  961.93
   104.7  944.64   117.6  940.85   217.9  934.56   270.7  934.53   346.6   932.4
   425.2928.2537   434.4  928.08   463.8928.2224   471.7  929.54   476.7  931.85
   487.3  940.17   505.7  951.29   528.4   971.1   557.8  975.35   565.3  978.49
   573.8  984.78   587.5  997.73   613.9 1012.95   633.3 1029.27   661.3 1048.75
   678.7 1055.16   707.1 1062.79   717.4 1068.35   741.9 1084.88   759.7 1092.65
#Mann= 7 ,-1,0
       0      .1       0     190     .06       0  328.88      .1       0
  368.88     .06       0   425.2    .045       0   463.8     .06       0
  563.65      .1       0
Bank Sta=425.2,463.8
XS Rating Curve= 0 ,0
Exp/Cntr(USF)=0,0
Exp/Cntr=0.3,0.1

Type RM Length L Ch R = 1 ,4298    ,305.9,305.9,305.9
XS GIS Cut Line= 2
1677001.44925655394154.7822731891677413.08934651394479.884389687
#Sta/Elev= 30
       0  993.88    14.5  985.32    37.3  973.79    51.6  967.99    64.6   965.3
    86.7  950.98   108.5   935.5   120.6  930.72   125.7  929.61     190  926.88
   259.5  927.38   267.4  925.19   270.8  924.77   274.3  925.18   282.2     929
   293.9  930.44   299.3  934.58   304.1  940.73   309.2  945.18   325.5  954.73
   360.2  969.85   381.9   983.9   390.8  988.53   407.5  996.38   421.8 1001.18
     436 1007.68   450.3 1016.71   477.4 1036.38   493.3 1046.05   524.5 1055.67
#Mann= 3 ,-1,0
       0      .1       0   267.4    .045       0   274.3      .1       0
Bank Sta=267.4,274.3
XS Rating Curve= 0 ,0
Exp/Cntr(USF)=0,0
Exp/Cntr=0.3,0.1

Type RM Length L Ch R = 1 ,3993    ,495.7,495.7,495.7
XS GIS Cut Line= 6
1676871.24684709394232.7738404271676913.41835067394326.425556004
1676953.78506784 394414.652741761676987.21741568394488.583040088
1677015.92372309394584.5792391751677089.98328626394829.894037262
#Sta/Elev= 30
       0 1023.21    24.7 1007.05    56.8  994.44    96.3  972.32     105  969.79
   121.4  967.69   144.6  958.62   154.6  952.23   184.2  927.93     193  923.68
     209  922.18   276.4  923.34   314.2  922.98   320.1  922.45   328.3919.9355
   330.9  919.29   337.2919.9429   355.5  927.73   365.1  928.12   393.6  932.33
   429.3  956.04     439  961.55   468.8  974.01   502.2  991.27   539.8 1005.17
     569 1019.74   589.9 1028.62   610.8 1032.16   623.4 1033.03   637.3 1031.97
#Mann= 5 ,-1,0
       0      .1       0  300.87     .05       0   328.3    .045       0
   337.2     .06       0  506.07      .1       0
Bank Sta=328.3,337.2
XS Rating Curve= 0 ,0
Exp/Cntr(USF)=0,0
Exp/Cntr=0.3,0.1

Type RM Length L Ch R = 1 ,3497    ,350.3,350.3,350.3
XS GIS Cut Line= 6
  1676470.534722394482.9065422561676536.02606083394564.758412674
1676596.40815793394648.0430230051676644.15314117394729.523831174
     1676681.928394836.0869382621676781.23160717395072.409300253
#Sta/Elev= 30
       0 1049.91    53.3 1020.56    85.8  995.44   104.5  987.41   124.3  981.95
   208.3   939.5   222.2  931.58   240.7  923.36   259.3  918.98   291.7  915.44
   343.5  912.37   357.7  912.48   363.5911.4553     369  910.91   377.9 911.424
     386  913.28   390.2  916.27   394.5  917.43     442  919.93   459.6  924.79
     477  925.33   481.4  927.24   490.2     935   508.3  946.42   520.3  952.54
   568.1  968.92   589.7  979.46   606.3  986.32   650.1  997.45   671.6 1004.56
#Mann= 6 ,-1,0
       0      .1       0   267.7     .05       0   363.5    .045       0
   377.9     .05       0  382.14     .06       0   485.2      .1       0
Bank Sta=363.5,377.9
XS Rating Curve= 0 ,0
Exp/Cntr(USF)=0,0
Exp/Cntr=0.3,0.1

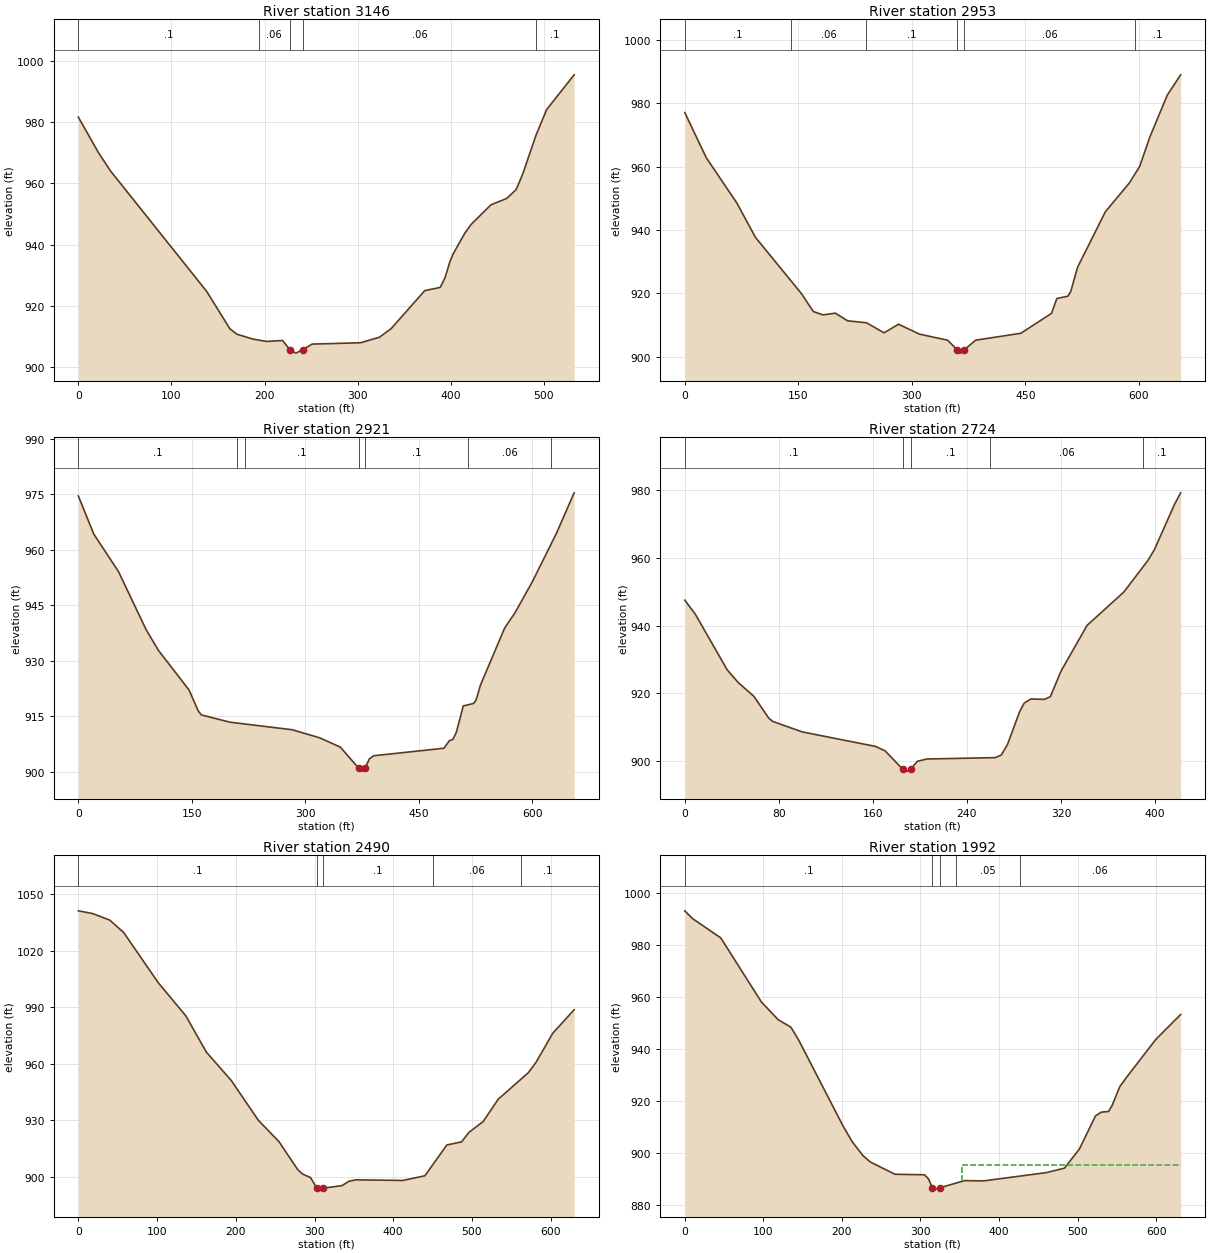
Type RM Length L Ch R = 1 ,3146    ,193.1,193.1,193.1
XS GIS Cut Line= 4
1676276.40137084394716.1096685811676338.38127075394889.185615493
1676470.52709508 394975.723588951676588.63973452395125.410894388
#Sta/Elev= 30
       0  981.63    21.7  969.99    34.5  964.08   137.8  924.76   162.8  912.52
   170.4  910.76   187.5  909.18     202   908.4   219.4  908.71   227.1 905.758
   233.7  904.59   241.1  905.71   251.1  907.54   303.1  907.97   323.3  909.77
     336   912.6     372  924.98   388.7  926.05   393.8   929.2   398.9  934.26
   402.5  936.95   414.7  943.55   421.8  946.59   443.2  953.01     460  955.07
   470.2  957.96   477.4  963.16   491.6  975.78     503  984.11   532.5  995.43
#Mann= 5 ,-1,0
       0      .1       0  193.84     .06       0   227.1    .045       0
   241.1     .06       0   491.8      .1       0
Bank Sta=227.1,241.1
XS Rating Curve= 0 ,0
Exp/Cntr(USF)=0,0
Exp/Cntr=0.3,0.1

Type RM Length L Ch R = 1 ,2953    ,32.4,32.4,32.4
XS GIS Cut Line= 6
1676203.89658227394760.5480873831676251.84329729395038.872920931
1676304.46774061395077.4641793641676326.68695001395114.886005724
 1676313.8231972395206.1017074751676463.51050264395287.961952636
#Sta/Elev= 30
       0  977.05    28.4  962.81      69  948.45    93.3  937.72   154.2  919.93
   169.8  914.31   182.6  913.25   198.9   913.8   215.1  911.38     240  910.77
   263.3   907.6   282.4   910.3   310.1  907.18   347.3  905.26   359.7902.2845
   364.8  901.19   369.1902.1967   384.3  905.27     444  907.45   484.5  913.73
   491.6  918.42   506.2  919.15   509.9   920.6     519  928.31   555.7  945.78
   587.4  954.87     601  960.07   614.7  969.51   637.5  982.57   655.1  988.96
#Mann= 6 ,-1,0
       0      .1       0     140     .06       0     240      .1       0
   359.7    .045       0   369.1     .06       0  594.46      .1       0
Bank Sta=359.7,369.1
XS Rating Curve= 0 ,0
Exp/Cntr(USF)=0,0
Exp/Cntr=0.3,0.1

Type RM Length L Ch R = 1 ,2921    ,197.5,197.5,197.5
XS GIS Cut Line= 6
1676176.99964457394776.3354203781676224.94635959395054.660253927
1676277.57080291 395093.251512361676299.79001231395130.673338719
 1676286.9262595 395221.889040471676436.61356494395303.749285632
#Sta/Elev= 30
       0  974.52    20.5   964.2      53  954.13    89.5  938.45   105.7  932.87
   146.3  922.12   158.5  916.46   162.6   915.4   200.2  913.44   282.4   911.4
   318.6  909.24   346.1  906.71   370.6  900.98   375.3  900.22   378.7     901
   384.6  903.54   390.4  904.38   483.1   906.4   490.2  908.43   494.9  908.79
   499.5  910.72   508.6  917.82   522.3   918.5   525.6  919.47   531.4  923.49
   563.3  938.88     577     943   599.8  951.34   631.7  964.44   655.1  975.37
#Mann= 7 ,-1,0
       0      .1       0     210     .06       0     220      .1       0
   370.6    .045       0   378.7      .1       0  514.46     .06       0
  624.46      .1       0
Bank Sta=370.6,378.7
XS Rating Curve= 0 ,0
Exp/Cntr(USF)=0,0
Exp/Cntr=0.3,0.1

Type RM Length L Ch R = 1 ,2724    ,233.3,233.3,233.3
XS GIS Cut Line= 2
1676013.27915425395140.6135113461676337.21183867395410.752320378
#Sta/Elev= 30
       0  947.52     8.9  943.41      36     927    45.4  923.24    58.8  919.14
    71.4  912.72    74.8  911.75    99.8  908.66   162.3  904.37   170.4  903.06
   185.2897.7291   189.4  897.08   192.2   897.7   197.9  899.98     206  900.66
   264.1  901.06   269.3  901.86   274.5  904.93   284.9  914.68   288.8  917.19
   294.5  918.37   305.9  918.25     311  919.05     320  926.55   342.2  940.08
   373.5  949.92   393.9   959.2   399.5  962.42   416.6  975.78   421.8  979.19
#Mann= 5 ,-1,0
       0      .1       0   185.2    .045       0   192.2      .1       0
     260     .06       0     390      .1       0
Bank Sta=185.2,192.2
XS Rating Curve= 0 ,0
Exp/Cntr(USF)=0,0
Exp/Cntr=0.3,0.1

Type RM Length L Ch R = 1 ,2490    ,498.5,498.5,498.5
XS GIS Cut Line= 6
1675715.78262259395291.7812368421675949.07710351395397.484765589
1676043.00736184395442.465974838 1676112.3802546395482.712285429
1676191.09597643395529.7915875911676272.68013084395583.402372763
#Sta/Elev= 30
       0 1041.13    17.9 1039.71    39.9 1036.21    57.5 1029.69   101.4 1003.07
   136.5  985.45   162.8  966.08   194.2  951.18   228.7  930.01   254.7  918.79
   278.7  903.85   284.7  901.55     295  899.63   302.9894.0175   305.7  893.51
   310.8  894.02   334.9  895.37   343.8   897.7   352.6  898.44   412.3  898.12
   440.2  900.58   468.1  916.93   486.8  918.57   496.1   923.6   514.2  929.36
   533.4  941.21   571.7  955.31   581.3  960.71   602.7  976.24   629.8  988.67
#Mann= 5 ,-1,0
       0      .1       0   302.9    .045       0   310.8      .1       0
  450.47     .06       0  562.19      .1       0
Bank Sta=302.9,310.8
XS Rating Curve= 0 ,0
Exp/Cntr(USF)=0,0
Exp/Cntr=0.3,0.1

Type RM Length L Ch R = 1 ,1992    ,498.8,498.8,498.8
XS GIS Cut Line= 6
1675580.71924442395567.057589173 1675658.6232881395631.001030833
1675725.18483476395690.8634439261675772.31072475395749.208799675
1675834.98448393395828.7109372621675970.61872709396055.860417336
#Sta/Elev= 30
       0  993.24     9.6  990.32    45.8  982.83    97.5   958.2   118.9  951.38
   135.1  948.51   145.4   943.3   201.3  910.59     213  904.52   226.8  899.11
   236.2  896.67   267.5  891.97   305.2  891.76   310.3  890.15     315886.7944
   318.8  886.25   324.5  886.75   356.1  889.52   380.5  889.42   460.5  892.61
   483.3  894.32   502.3  901.69   522.7  914.38   530.1  915.84   539.4   916.1
     544  918.48   553.7  925.66   562.5  929.31   599.5   943.8   631.1  953.38
#Mann= 5 ,-1,0
       0      .1       0     315    .045       0   324.5      .1       0
  345.31     .05       0  426.54     .06       0
#XS Ineff= 2 , 0
                          352.26          895.44
Permanent Ineff=
       F       F
Bank Sta=315,324.5
XS Rating Curve= 0 ,0
Exp/Cntr(USF)=0,0
Exp/Cntr=0.3,0.1

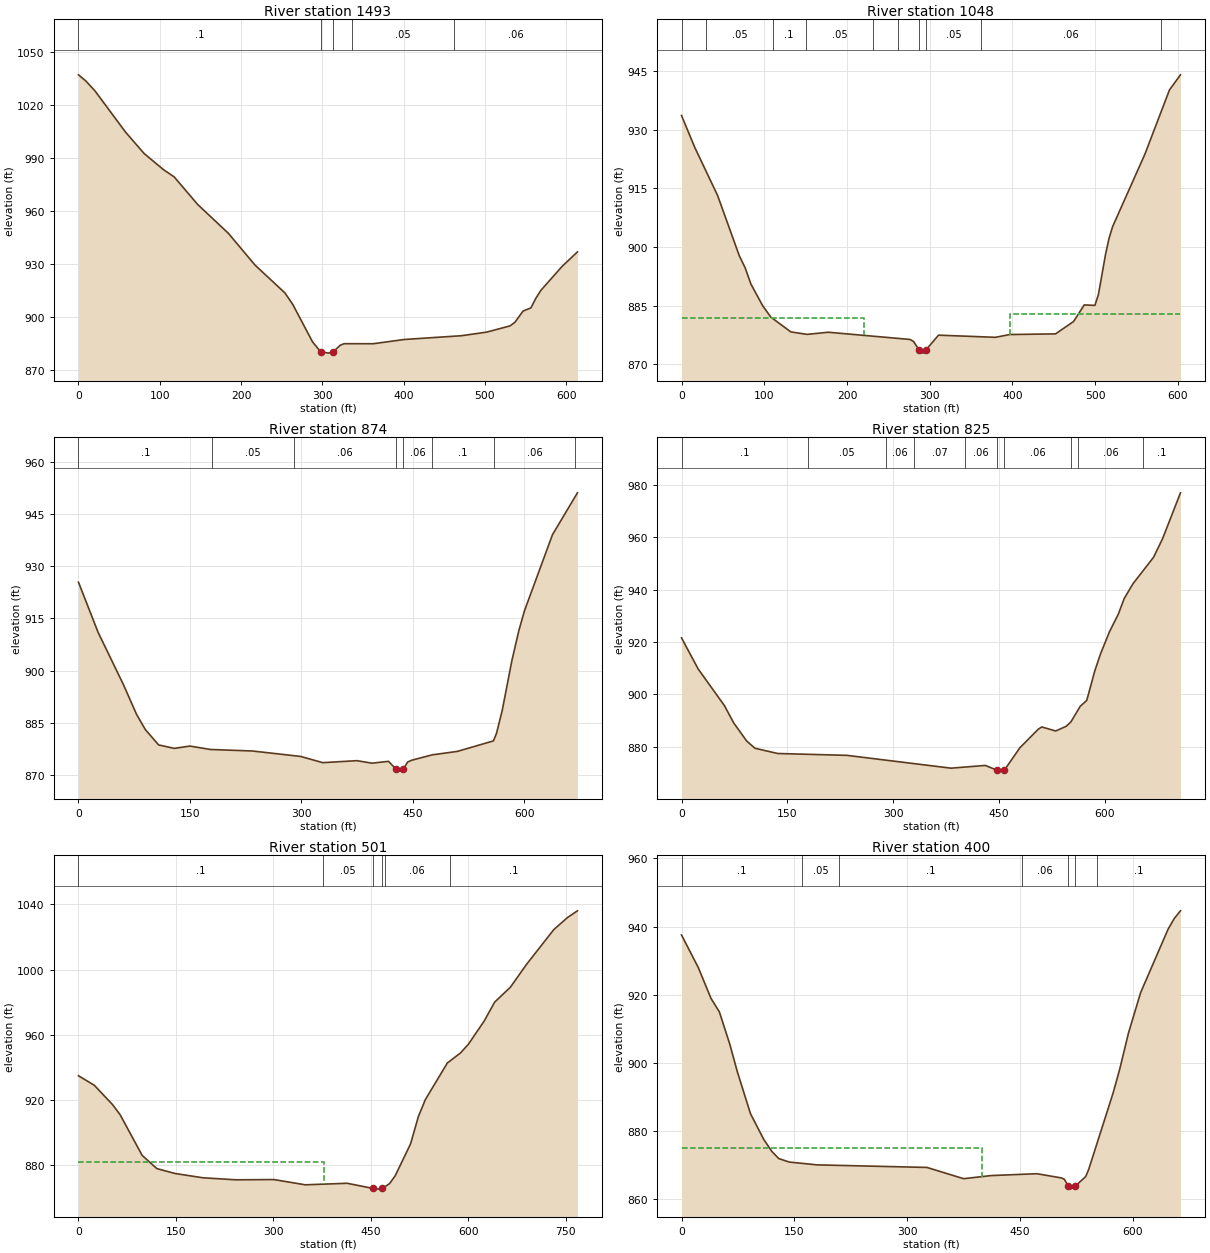
Type RM Length L Ch R = 1 ,1493    ,444.7,444.7,444.7
XS GIS Cut Line= 6
1675251.38033618395984.9370027481675400.40366018396088.105103508
1675544.28788684396187.7157966791675604.52989234396232.461114004
1675674.33060576396286.0502456721675748.76910518396344.160037592
#Sta/Elev= 30
       0 1037.04     8.9 1033.64    20.4 1027.88    57.7 1004.69    80.7  992.48
   104.7  983.27   117.7  979.23   146.8  963.51   184.2  947.36   217.1   929.3
   253.9  913.52   263.6  906.97   287.9  885.76   297.7  880.28   307.4  879.41
   313.6  880.28   322.2  883.96   326.8  884.75   362.4  884.73   400.9  887.14
     471  889.27   502.4  891.34   530.9  894.86   536.8  896.91   546.9  903.28
   556.5  905.04   562.3  910.28   568.8     915   594.8  928.52   613.7  936.75
#Mann= 5 ,-1,0
       0      .1       0   297.7    .045       0   313.6      .1       0
  336.25     .05       0  461.29     .06       0
Bank Sta=297.7,313.6
XS Rating Curve= 0 ,0
Exp/Cntr(USF)=0,0
Exp/Cntr=0.3,0.1

Type RM Length L Ch R = 1 ,1048    ,173.9,173.9,173.9
XS GIS Cut Line= 4
1675106.75273561396509.3399103371675232.35840279 396594.52076509
1675444.58866802396510.7836536381675652.48770335396591.633278488
#Sta/Elev= 30
       0  933.68    16.1  925.47    43.6  913.21    69.8  897.79      77  894.64
    83.9  890.51    98.3   884.9     108  882.05   132.1  878.28   151.8  877.64
   177.3  878.19   276.2  876.34   280.5  875.81     287873.6722   291.9  872.84
   295.5873.6864   310.6  877.44   379.4  876.89   396.6   877.6     452  877.77
   473.8  880.93   486.7  885.18   499.6  885.07   503.9  887.89   512.5   898.2
   516.7  902.24     521  905.24   560.1  923.82   589.7  940.23     603   944.1
#Mann= 10 ,-1,0
       0      .1       0      30     .05       0     110      .1       0
     150     .05       0  231.76      .1       0  261.76     .05       0
     287    .045       0   295.5     .05       0  361.76     .06       0
  579.92      .1       0
#XS Ineff= 2 ,-1
       0  220.42  881.72  397.56602.9839   882.9
Permanent Ineff=
       F       F
Bank Sta=287,295.5
XS Rating Curve= 0 ,0
Exp/Cntr(USF)=0,0
Exp/Cntr=0.3,0.1

Type RM Length L Ch R = 1 ,874     ,49.1,49.1,49.1
XS GIS Cut Line= 4
1675067.77166648396623.3956311081675396.94513909396759.107501393
1675505.22588666396611.8456847011675632.27529714396650.826753825
#Sta/Elev= 30
       0  925.39    26.3  911.07    60.9  895.83    78.2  887.46      90  883.11
   107.9  878.71   128.9  877.72   149.9  878.38   177.8   877.4   233.9  876.97
   298.9  875.41   328.9  873.62   374.9  874.19   395.2  873.47   417.4     874
   427.1871.8317   433.7  871.19   437.4  871.83   443.1   873.8   448.6  874.32
   476.2  875.86     510  876.85   558.6  879.86   562.8  882.06   570.5  888.65
   583.3  902.77   592.9  911.57   600.4   917.2   638.1  939.03   671.7  951.04
#Mann= 8 ,-1,0
       0      .1       0     180     .05       0     290     .06       0
   427.1    .045       0   437.4     .06       0  476.05      .1       0
  558.84     .06       0  668.84      .1       0
Bank Sta=427.1,437.4
XS Rating Curve= 0 ,0
Exp/Cntr(USF)=0,0
Exp/Cntr=0.3,0.1

Type RM Length L Ch R = 1 ,825     ,324.6,324.6,324.6
XS GIS Cut Line= 4
1675064.16230823396639.2768074181675425.09813346396792.313597314
1675533.37888103396645.0517806221675660.42829151396684.032849746
#Sta/Elev= 30
       0  921.55    23.7  909.65    60.8  895.72    74.1  889.05    92.5  882.16
   104.2  879.41   136.4  877.41   234.6   876.7   382.3  871.81   430.9  872.86
   447.6 871.028   451.3  870.68   457.9  871.04   479.9  879.58   505.6  886.58
   510.9  887.55   530.8     886   545.7  887.81   552.4  889.52   565.5  895.42
   574.8  897.69   586.2  908.97   594.4  915.51     607  923.88   619.5  930.58
   627.9  936.58   640.4  942.24   669.5  952.32   682.3   959.4   707.7  976.93
#Mann= 10 ,-1,0
       0      .1       0     180     .05       0     290     .06       0
     330     .07       0  402.04     .06       0   447.6    .045       0
   457.9     .06       0  552.04      .1       0  562.04     .06       0
  654.83      .1       0
Bank Sta=447.6,457.9
XS Rating Curve= 0 ,0
Exp/Cntr(USF)=0,0
Exp/Cntr=0.3,0.1

Type RM Length L Ch R = 1 ,501     ,101,101,101
XS GIS Cut Line= 6
1674935.14651621396806.8911209261675107.59387834396984.467155918
1675269.33207193397007.7883035091675368.08449909397023.728888422
1675528.78660551397047.8338270931675618.86418125397075.916120008
#Sta/Elev= 30
       0  934.96    24.4   929.1    52.5  917.23    64.1  911.06      98  886.14
   120.7  878.03   148.9  875.02   191.9  872.41   242.1  871.18   300.6  871.33
   349.1  868.11   413.4  869.06   453.8865.8621   462.9  865.47   467.6  865.87
   478.6  868.83   487.3   873.6     511  893.19   523.1  910.02   533.8  920.36
   567.6  942.75   587.9  948.95     600  954.27   624.3  968.47   640.4  980.05
   664.7  989.25   689.6 1003.28   731.4 1024.51   752.4 1031.88   767.8 1036.02
#Mann= 6 ,-1,0
       0      .1       0  375.52     .05       0   453.8    .045       0
   467.6     .05       0  470.94     .06       0  570.97      .1       0
#XS Ineff= 2 , 0
          377.97  881.84
Permanent Ineff=
       F       F
Bank Sta=453.8,467.6
XS Rating Curve= 0 ,0
Exp/Cntr(USF)=0,0
Exp/Cntr=0.3,0.1

Type RM Length L Ch R = 1 ,400     ,203.3,203.3,203.3
XS GIS Cut Line= 3
1674925.75131401396825.2631937741675074.26918738397076.691089627
1675440.30142646397138.670989535
#Sta/Elev= 30
       0  937.53    22.4  927.95    39.2  918.94    50.3  915.01    64.2  905.51
    74.2  897.44    91.7  885.14   109.3  877.61   119.9  874.13   129.2  871.99
   143.2  870.96   180.3  870.13   326.3  869.38     375  866.08   411.4  866.99
   472.4  867.54   505.1   866.3   508.9  865.93   514.2  863.88     517  863.02
   523.3 863.886   537.3  866.69   541.4  868.86   573.8  891.24   582.6  898.23
   594.1  908.72   610.3  920.61   646.8  939.22     655  942.36   663.3  944.62
#Mann= 7 ,-1,0
       0      .1       0     160     .05       0     210      .1       0
  452.02     .06       0   514.2    .045       0   523.3     .06       0
  552.02      .1       0
#XS Ineff= 2 , 0
          400.11  875.07
Permanent Ineff=
       F       F
Bank Sta=514.2,523.3
XS Rating Curve= 0 ,0
Exp/Cntr(USF)=0,0
Exp/Cntr=0.3,0.1

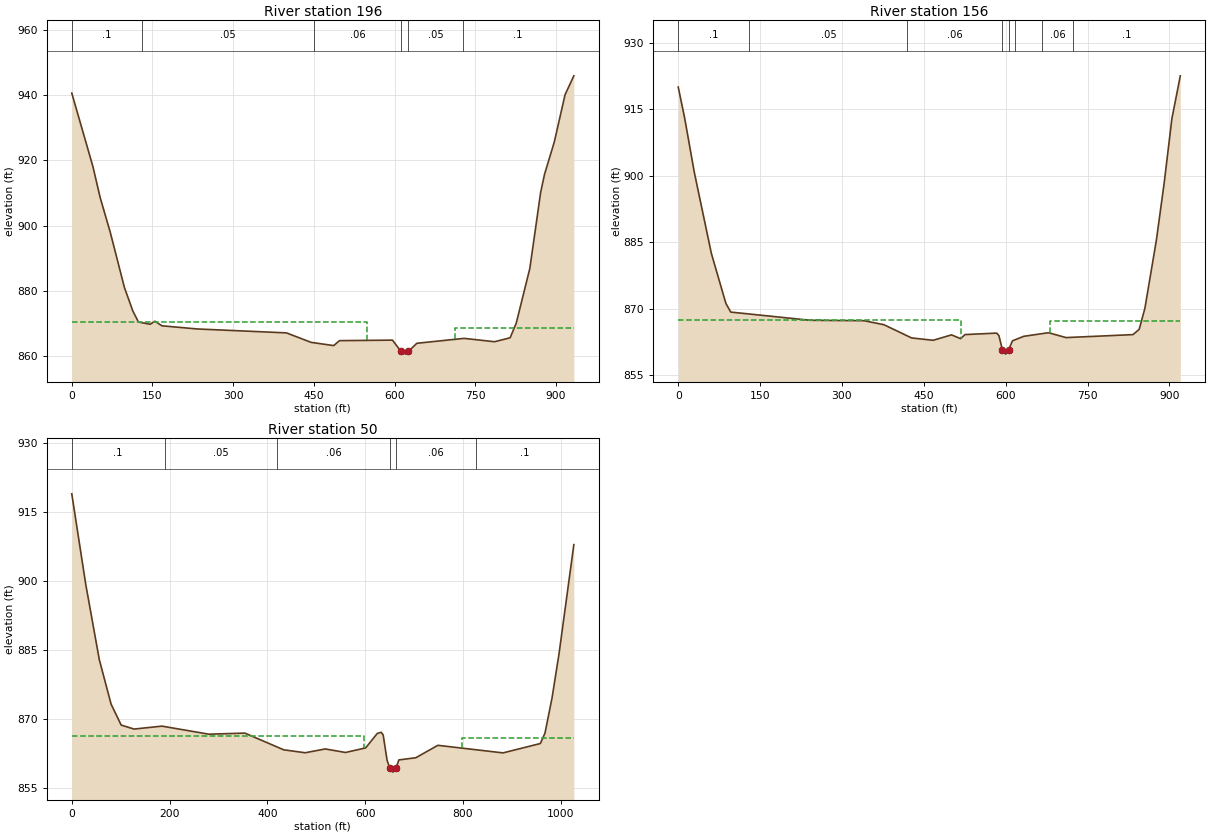
Type RM Length L Ch R = 1 ,196     ,40.3,40.3,40.3
XS GIS Cut Line= 4
1674892.44348002396846.814906923 1675076.0443156397268.979885541
 1675325.1333473397327.4514892281675497.03986214397195.305664896
#Sta/Elev= 30
       0  940.68    39.3  918.11    52.7  908.63    71.7  897.82    97.8  880.98
   113.5  873.73     124  870.34   145.8  869.67   154.5  870.61   167.6  869.19
   233.1  868.22   398.8  867.02   444.9   864.1   486.7  863.11   497.4  864.63
     596  864.79   611.4   861.4   620.7  860.49   625.7861.3281   641.2  863.82
     729  865.33   785.6   864.3   814.6  865.51     826  870.03   851.2   886.8
   871.3  910.15   878.5  915.71   896.6  925.61   916.7  940.19     933  945.98
#Mann= 6 ,-1,0
       0      .1       0     130     .05       0     450     .06       0
   611.4    .045       0   625.7     .05       0  726.22      .1       0
#XS Ineff= 2 , 0
          548.46  870.29  712.44          868.58
Permanent Ineff=
       F       F
Bank Sta=611.4,625.7
XS Rating Curve= 0 ,0
Exp/Cntr(USF)=0,0
Exp/Cntr=0.3,0.1

Type RM Length L Ch R = 1 ,156     ,106.2,106.2,106.2
XS GIS Cut Line= 4
1674878.99501117396885.9908813931675083.64562408397305.816995864
1675311.68487846397366.6274636981675483.59139329397234.481639366
#Sta/Elev= 30
       0  920.05    11.7  913.12    29.5   900.8    60.7  882.54    87.4  871.23
    96.3   869.3   242.1  867.45   340.3  867.36   376.8  866.46   427.6  863.47
   467.1  862.94   500.7  864.16   517.2  863.32   525.5  864.23   583.4  864.56
   587.6  863.99   593.8  860.84     600  859.82   605.4860.8448   612.4  862.82
   633.1  863.84   678.4  864.65   710.6  863.55   833.2  864.22   844.6  865.42
     855  870.15     876  885.48   890.3  898.37   904.5  912.94   919.9  922.59
#Mann= 8 ,-1,0
       0      .1       0     130     .05       0     420     .06       0
   593.8    .045       0   605.4     .06       0  617.05     .05       0
  667.05     .06       0  723.06      .1       0
#XS Ineff= 2 ,-1
  -57.27  518.57867.5089  680.81919.8862  867.28
Permanent Ineff=
       F       F
Bank Sta=593.8,605.4
XS Rating Curve= 0 ,0
Exp/Cntr(USF)=0,0
Exp/Cntr=0.3,0.1

Type RM Length L Ch R = 1 ,50      ,,,
XS GIS Cut Line= 5
1674843.91204896396895.3463379831675146.79495606397440.301684343
1675223.39275689397444.3946966011675278.94078039397408.727018352
1675497.62457818397267.225737431
#Sta/Elev= 30
       0  918.99    28.8  899.14    56.3  882.88    80.4  873.18     101  868.62
   127.5  867.75   184.4  868.39   280.5  866.63     354  866.87   433.4  863.23
   477.3  862.59   518.5  863.42   559.7  862.65   600.9  863.64   624.8   866.8
   632.8  867.04   636.8  866.47   644.8  860.95   650.4 859.235   656.8  858.37
   662.8  859.21   668.9  861.03   703.5   861.5   748.6  864.21   881.9  862.56
   958.2   864.6   967.7  866.88     982  874.46   996.3  884.07  1026.7  907.92
#Mann= 6 ,-1,0
       0      .1       0     190     .05       0     420     .06       0
   650.4    .045       0   662.8     .06       0  826.19      .1       0
#XS Ineff= 2 , 0
          596.98  866.15  797.12          865.84
Permanent Ineff=
       F       F
Bank Sta=650.4,662.8
XS Rating Curve= 0 ,0
Exp/Cntr(USF)=0,0
Exp/Cntr=0.3,0.1
LCMann Table=0

Chan Stop Cuts=-1
Use User Specified Reach Order=0
Composite Channel Slope=5